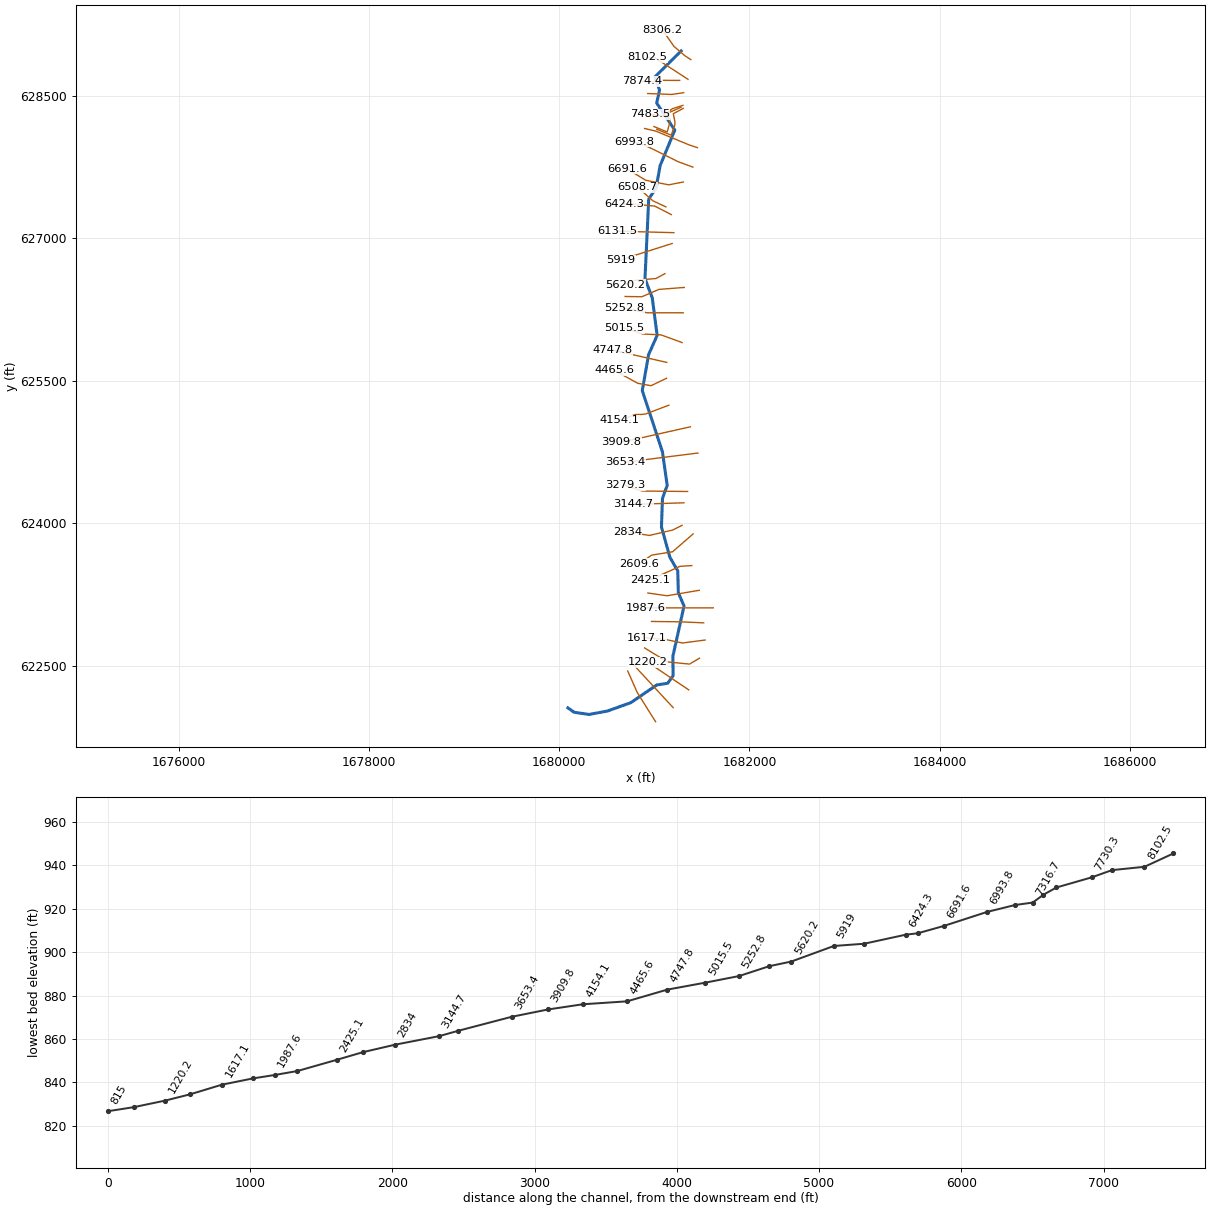
--- CMPRN.prj (project) ---

Proj Title=CMPRN
Current Plan=p01
Default Exp/Contr=0,0
English Units
Geom File=g01
Flow File=f01
Plan File=p01
BEGIN DESCRIPTION:
END DESCRIPTION:
DSS Export Rating Curves= 0
DSS Export Rating Curve Sorted= 0
DSS Export Volume Flow Curves= 0
DXF Filename=..\..\..\..\..\Engineering\Hydraulics\CMPRN\CMPRN.
DXF OffsetX= 0
DXF OffsetY= 0
DXF ScaleX= 0
DXF ScaleY= 0

--- CMPRN.p01 (plan) ---

Plan Title=Floodplain
Program Version=4.00
Geom File=g01
Flow File=f01
K Sum by GR=0
Std Step Tol=0.01
Critical Tol=0.01
Num of Std Step Trials=20
Max Error Tol=0.3
Flow Tol Ratio=0.001
Split Flow NTrial=30
Split Flow Tol=0.02
Split Flow Ratio=0.02
Log Output Level=0
Friction Slope Method=1
Unsteady Friction Slope Method=2
Unsteady Bridges Friction Slope Method=1
Global Log Level=0
CheckData=False
Run HTab=0
Run UNet=0
Run PostProcess=0
UNET Theta=0
UNET Theta Warmup=0
UNET ZTol=0
UNET ZSATol=0
UNET MxIter=0
UNET MaxInSteps=0
UNET DtIC=0
UNET DtMin=0
UNET MaxCRTS=0
UNET WFStab=0
UNET SFStab=0
UNET WFX=0
UNET SFX=0
UNET DSS MLevel=0
UNET DZMax Abort=0
UNET Convert EG Bridges=0
UNET Use Existing IB Tables=0
UNET Froude Limit=0
UNET Froude Power=0
Write IC File=0
Echo Input=False
Echo Output=False
Write Detailed=0

--- CMPRN.f01 (steady flow) ---

Flow Title=NFF Regression Equation
Program Version=4.10
Number of Profiles= 1
Profile Names=P100yr
River Rch & RM=CMPRN,Main            ,8306.2
 871.485
River Rch & RM=CMPRN,Main            ,7730.3
921.7441
River Rch & RM=CMPRN,Main            ,4465.6
1020.263
River Rch & RM=CMPRN,Main            ,495.1
 1131.66
River Rch & RM=CMPRN,Main            ,199.7
1136.562
Boundary for River Rch & Prof#=CMPRN,Main            , 1
Up Type= 0
Dn Type= 3
Dn Slope=0.03
DSS Import GetInterval= 0
DSS Import GetPeak= 0
DSS Import FillOption= 0

--- CMPRN.g01 (geometry) ---

Geom Title=2003 WVU SAMB 3 Meter DEM
Program Version=4.10

River Reach=CMPRN           ,Main
Reach XY= 30
     1681281.705      628969.505      1681006.01      628696.936
     1681053.927      628556.311     1681023.892      628420.634
     1681214.517      628135.634     1681060.611      627764.149
     1681016.861      627524.045     1680940.298      627412.327
     1680900.802      626574.241     1680977.364      626371.897
     1681028.667      625976.584     1680938.967      625775.031
     1680872.417      625396.116     1681084.599      624751.366
     1681134.599      624397.825     1681084.599      624262.755
     1681074.139      623962.017     1681162.781      623642.639
      1681245.42      623499.475      1681251.93      623269.006
     1681311.653      623129.475     1681194.292      622601.697
      1681196.68      622397.043     1681139.604      622317.235
     1681024.956      622299.551     1680752.024       622113.46
     1680507.011      622025.515     1680311.753      621988.933
     1680155.465      622012.457     1680090.409      622058.508

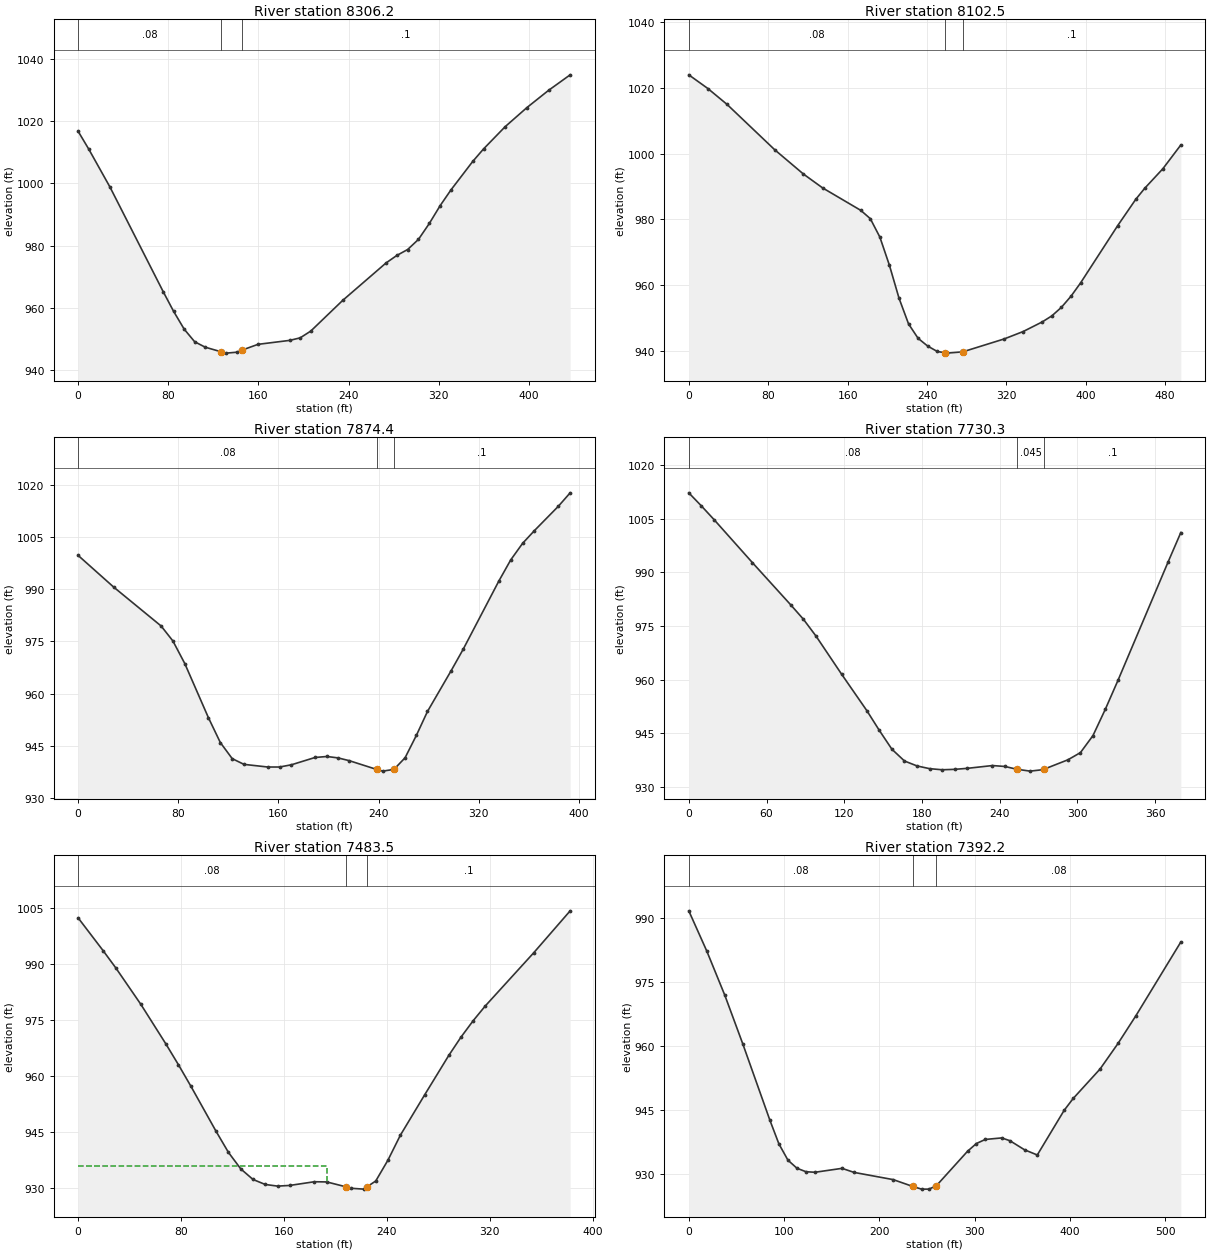
Type RM Length L Ch R = 1 ,8306.2  ,200.5,203.7,206.7
XS GIS Cut Line= 4
     1681383.125       628877.45      1681320.19      628918.903
     1681206.361      629016.236     1681084.514      629189.082
#Sta/Elev= 30
       0  1016.7     9.4 1010.99    28.3  998.77    75.4  965.28    84.7  958.92
    94.1  953.19   103.4  949.15   112.8   947.4   126.4945.9803   131.5   945.5
   140.9   945.8   145.4 946.467   159.6  948.32   187.7  949.59     197   950.4
   206.4  952.57   234.7  962.41   273.2  974.44   282.8  976.86   292.4  978.76
     302  982.02   311.6  987.11   321.3  992.88   330.9  997.93   350.1 1007.01
   359.7 1011.03   378.9 1018.18   398.2 1024.31   417.4 1029.84   436.6 1034.83
#Mann= 3 , 0 , 0
       0     .08       0   126.4    .045       0   145.4      .1       0
Bank Sta=126.4,145.4
XS Rating Curve= 0 ,0
Exp/Cntr=0.3,0.1

Type RM Length L Ch R = 1 ,8102.5  ,210.3,228.1,245.1
XS GIS Cut Line= 3
     1681353.798      628670.277     1681006.515      628895.566
     1680924.972      628901.727
#Sta/Elev= 30
       0 1023.98    19.2 1019.82    38.5    1015    86.6 1001.18   115.5   993.8
   134.8  989.59   173.3  982.75   182.9  980.22   192.5  974.63   202.2  965.99
   211.8  956.04   221.4  948.22     231  943.84   240.7  941.47   250.3  939.84
   257.9 939.438   259.9  939.33   275.9939.7097   317.7  943.64   336.9   945.9
   356.2  948.84   365.8  950.67   375.4  953.26   385.1  956.65   394.7  960.68
   432.1  978.11   450.3  986.11   459.4  989.49   477.6  995.41   495.7 1002.64
#Mann= 3 , 0 , 0
       0     .08       0   257.9    .045       0   275.9      .1       0
Bank Sta=257.9,275.9
XS Rating Curve= 0 ,0
Exp/Cntr=0.3,0.1

Type RM Length L Ch R = 1 ,7874.4  ,148.5,144.1,138.8
XS GIS Cut Line= 4
     1681265.937        628658.7      1681067.14      628659.884
     1680988.216      628645.143     1680874.271       628648.11
#Sta/Elev= 30
       0  999.69    28.4   990.6    66.3  979.44    75.7  975.15    85.2  968.67
   104.1  953.12   113.6     946   123.1  941.38   132.5  939.74   151.5  938.98
   160.9  938.98   170.4  939.62   189.3  941.72   198.8     942   207.7  941.59
   216.6   940.8   238.6938.2758   243.4   937.8   252.3   938.3   261.2  941.63
   270.2  948.04   279.1  954.92   298.1  966.67   307.6  972.75   336.1  992.33
   345.6   998.4   355.1 1003.16   364.6 1006.83   383.6 1013.77   393.1 1017.65
#Mann= 3 , 0 , 0
       0     .08       0   238.6    .045       0   252.3      .1       0
Bank Sta=238.6,252.3
XS Rating Curve= 0 ,0
Exp/Cntr=0.3,0.1

Type RM Length L Ch R = 1 ,7730.3  ,231.6,246.8,261.4
XS GIS Cut Line= 3
     1681308.716      628530.047     1681182.394      628511.179
     1680930.472      628520.815
#Sta/Elev= 30
       0 1012.27     9.8 1008.58    19.6 1004.74    49.1  992.75    78.6  980.98
    88.4  976.95    98.2  972.21   117.9  961.58   137.4  951.38   147.1  945.82
   156.8  940.56   166.5  937.27   176.2  935.89   185.9  935.13   195.6  934.82
   205.3  934.94     215  935.22   234.4     936   244.1  935.74   253.1934.9698
   263.5  934.44   273.2  934.84   274.4935.0033   292.6   937.6   302.3  939.61
     312  944.38   321.6   951.8   331.4  959.91   370.1  993.03   379.8 1001.16
#Mann= 3 , 0 , 0
       0     .08       0   253.1    .045       0   274.4      .1       0
Bank Sta=253.1,274.4
XS Rating Curve= 0 ,0
Exp/Cntr=0.3,0.1

Type RM Length L Ch R = 1 ,7483.5  ,33.2,91.2,115.7
XS GIS Cut Line= 4
     1681300.659      628396.548     1681189.212      628361.515
     1681081.375      628282.695     1680950.833      628301.929
#Sta/Elev= 30
       0 1002.47    19.5  993.65    29.2   989.1    48.7  979.32    68.2  968.69
    77.9  963.15    87.6  957.38   107.1  945.34   116.8  939.64   126.4  935.21
   135.9  932.38   145.4  931.04     155   930.6   164.5  930.78   183.6  931.77
   193.2  931.72   208.3930.3936   212.2  930.02   221.8  929.79   224.3930.3633
   231.3  931.97   240.8  937.57   250.4  944.22   269.2  954.99   288.1  965.64
   297.5   970.5     307  974.91   316.4  978.86   354.1  993.13   382.4 1004.36
#Mann= 3 , 0 , 0
       0     .08       0   208.3    .045       0   224.3      .1       0
#XS Ineff= 2 , 0
       0   193.2     936               0
Permanent Ineff=
       F       F
Bank Sta=208.3,224.3
XS Rating Curve= 0 ,0
Exp/Cntr=0.3,0.1

Type RM Length L Ch R = 1 ,7392.2  ,107.5,75.5,118.1
XS GIS Cut Line= 6
     1681281.215       628377.45     1681134.255       628311.97
     1681157.631      628255.202     1681162.493      628218.049
     1681134.628      628116.639     1680995.166      628173.913
#Sta/Elev= 30
       0  991.68    18.9  982.25    37.9  971.86    56.8  960.44    85.2  942.59
    94.6  937.08   104.1  933.26   113.6  931.36     123  930.55   132.5  930.42
   160.9  931.34   173.5  930.39   214.6   928.7   235.3  927.09   244.4  926.47
   252.2  926.47     260  927.28   292.7  935.35     302  937.16   311.3  938.11
   328.6  938.47   337.2  937.81   352.5  935.69   365.9  934.47   394.1  944.93
   403.6  947.71   431.8  954.61   450.7  960.61   469.5  967.12   516.6  984.37
#Mann= 3 , 0 , 0
       0     .08       0   235.3    .045       0     260     .08       0
Bank Sta=235.3,260
XS Rating Curve= 0 ,0
Exp/Cntr=0.3,0.1

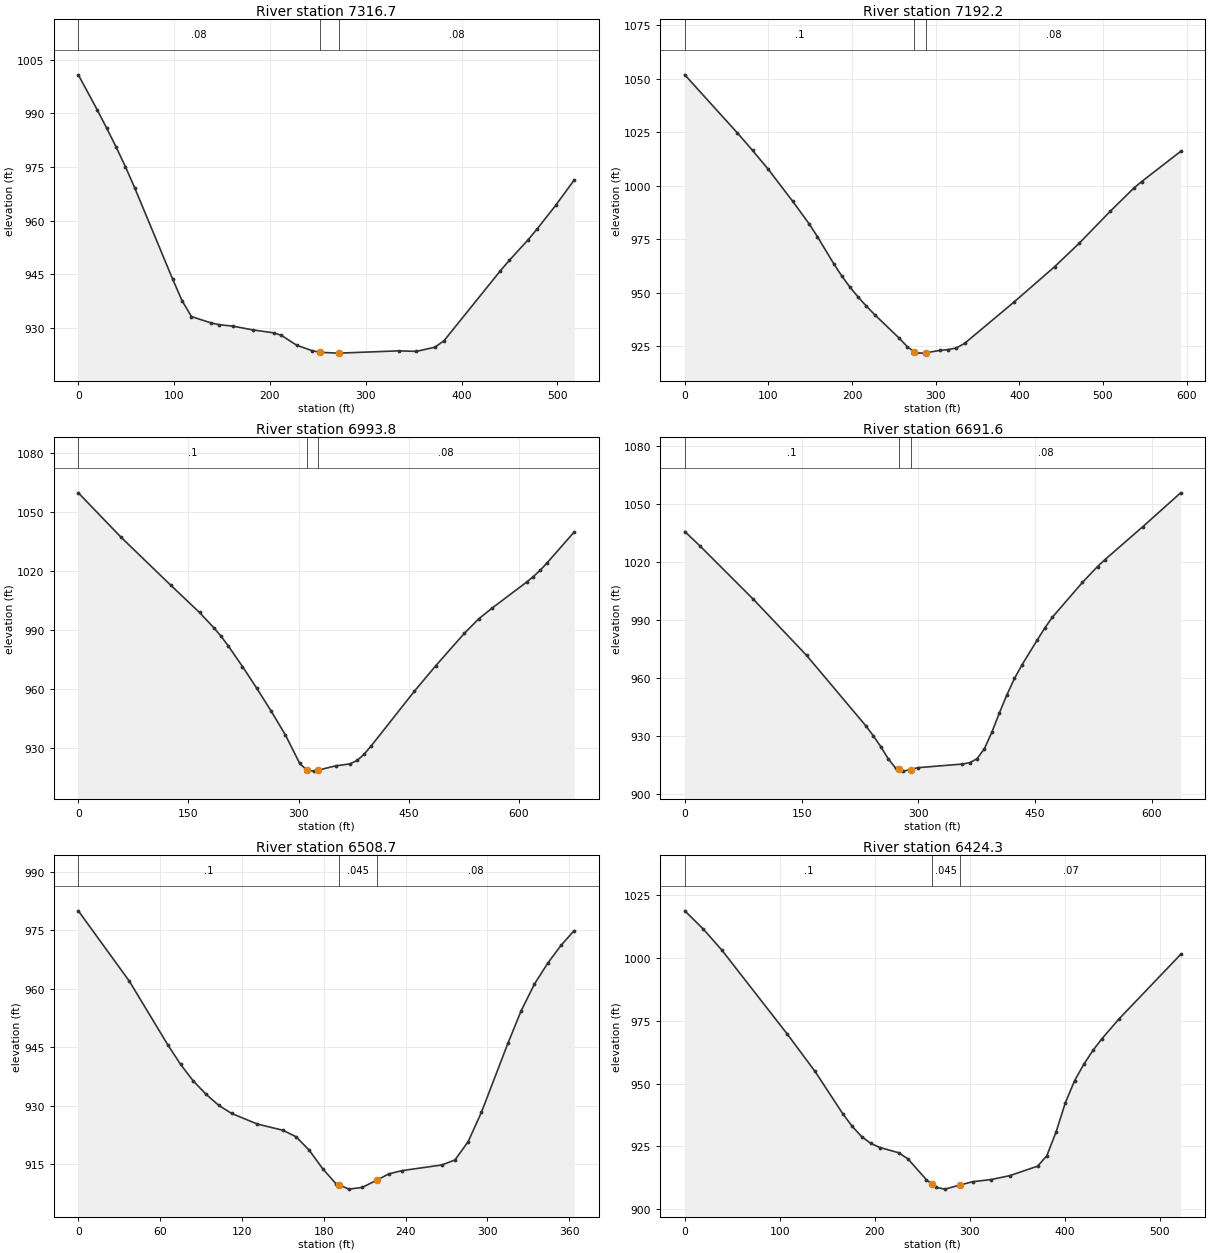
Type RM Length L Ch R = 1 ,7316.7  ,173.6,124.5,34.2
XS GIS Cut Line= 6
     1681302.877      628364.306     1681198.711      628308.751
     1681215.618      628224.646      1681215.27      628192.355
     1681176.624      628082.759     1681024.038      628144.937
#Sta/Elev= 30
       0 1000.82    19.7  991.02    29.5  985.93    39.4  980.63    49.2  975.04
      59  969.05    98.4  943.61   108.2  937.57   118.1  933.08   138.6   931.3
   146.3  930.83   161.5  930.39   181.9  929.36   203.9  928.52   211.8  927.84
   227.9  925.05   244.2  923.52   252.2  923.07   270.8  922.84     272  922.84
   334.5  923.48   352.8  923.33   372.2   924.5   381.8  926.36     440  945.75
   449.7  948.81   469.1  954.49   478.8  957.62   498.2  964.25   517.5  971.34
#Mann= 3 , 0 , 0
       0     .08       0   252.2    .045       0     272     .08       0
Bank Sta=252.2,272
XS Rating Curve= 0 ,0
Exp/Cntr=0.3,0.1

Type RM Length L Ch R = 1 ,7192.2  ,199.8,198.5,196.7
XS GIS Cut Line= 4
     1681452.613      627951.364      1681367.13      627979.628
     1681014.683      628125.513     1680896.489      628153.158
#Sta/Elev= 30
       0 1051.73      63 1024.54      81 1016.43    99.8 1007.59   129.2  992.56
   148.7  982.11   158.5  976.17   178.1   963.5   187.8   957.7   197.6  952.48
   207.4  947.86   217.2  943.64     227  939.71   256.3  928.73   266.1  924.71
   274.6922.2144   275.9  921.83   285.6  921.71   288.6   921.9   305.2  922.99
     315  923.36   324.8  924.13   334.6  926.26   393.2  945.42   442.1  962.05
   471.5     973   508.8  988.01   536.8  998.75   546.2 1001.83   592.9 1015.96
#Mann= 3 , 0 , 0
       0      .1       0   274.6    .045       0   288.6     .08       0
Bank Sta=274.6,288.6
XS Rating Curve= 0 ,0
Exp/Cntr=0.3,0.1

Type RM Length L Ch R = 1 ,6993.8  ,296.2,302.2,308.1
XS GIS Cut Line= 4
     1681405.233      627746.507     1681250.358      627803.628
     1680909.482      627972.588     1680785.815      628012.255
#Sta/Elev= 30
       0 1059.97    58.3 1037.35   126.2  1012.9   165.1  999.14   184.6  991.36
   194.3   987.1   204.1  982.25   223.6  971.67   243.1  960.61   262.6  949.05
   282.1  936.88   301.6  922.37   311.7 918.868   321.2  918.49   326.2918.9568
   350.4  921.16   369.9  922.18   379.7   923.9   389.4  927.12   399.2  931.44
   457.7  959.09     487  972.14     526  988.61   545.5  995.95   564.1  1001.5
   610.5 1014.55   619.7 1017.37     629 1020.57   638.3 1024.27   675.4 1040.05
#Mann= 3 , 0 , 0
       0      .1       0   311.7    .045       0   326.2     .08       0
Bank Sta=311.7,326.2
XS Rating Curve= 0 ,0
Exp/Cntr=0.3,0.1

Type RM Length L Ch R = 1 ,6691.6  ,195.1,182.9,170.7
XS GIS Cut Line= 4
     1681304.432       627590.32     1681150.938      627560.467
     1680908.184      627608.829      1680709.43      627729.982
#Sta/Elev= 30
       0 1035.95    19.6 1028.46      88 1000.93   156.4  971.89   232.5  935.48
     242  930.37   251.6  924.77   261.1  918.52   270.6  913.66   274.9912.9352
   280.1  912.06   289.9912.8516   299.2  913.83   356.3  915.72   365.8  916.41
   375.3  918.47   384.8  923.71   394.4  932.29   403.9  942.08   413.6   951.5
   423.3  959.96     433  967.02   452.4  979.75   462.1  985.95   471.8  991.55
   510.6 1009.63     530 1017.86   539.7 1021.48   588.2 1038.48   636.7 1055.96
#Mann= 3 , 0 , 0
       0      .1       0   274.9    .045       0   289.9     .08       0
Bank Sta=274.9,289.9
XS Rating Curve= 0 ,0
Exp/Cntr=0.3,0.1

Type RM Length L Ch R = 1 ,6508.7  ,69.8,84.4,98.6
XS GIS Cut Line= 3
     1681120.384       627328.87     1680984.507      627392.241
     1680824.212      627533.595
#Sta/Elev= 30
       0  979.98    37.5  961.91    65.6  945.66      75  940.64    84.3  936.39
    93.7  932.98   103.1  930.12   112.4  928.08   131.2  925.37   149.9  923.78
   159.6  922.13   169.4  918.63   179.1  913.96   188.8  910.12     191909.7941
   198.5  908.69   208.2  909.13   218.7910.9568   227.6  912.59   237.4  913.43
   266.5  914.88   276.2  916.16   285.9  920.88   295.6  928.38   315.1  946.12
   324.8  954.43   334.5  961.23   344.2  966.55   353.9  971.11   363.6  974.92
#Mann= 3 , 0 , 0
       0      .1       0     191    .045       0   218.7     .08       0
Bank Sta=191,218.7
XS Rating Curve= 0 ,0
Exp/Cntr=0.3,0.1

Type RM Length L Ch R = 1 ,6424.3  ,291.3,292.8,294.2
XS GIS Cut Line= 4
     1681177.837      627247.278     1681003.575      627336.781
      1680770.79      627359.133     1680678.705      627357.521
#Sta/Elev= 30
       0  1018.6    19.6 1011.31    39.2  1002.9   107.8  969.67   137.1   954.8
   166.5  937.88   176.3  932.94   186.1  928.93   195.9  926.17   205.6  924.55
   225.1   922.5   234.9  920.05   254.4  911.74   260.1909.9926   264.1  908.76
   273.8  908.04     290909.7177   303.1  910.99   322.6  911.86   342.1  913.39
   371.3  917.16     381  921.24   390.8  930.74   400.5  942.28   410.3  951.14
     420  957.66   429.8  963.26     439  967.76   457.4   975.8   521.9 1001.27
#Mann= 3 , 0 , 0
       0      .1       0   260.1    .045       0     290     .07       0
Bank Sta=260.1,290
XS Rating Curve= 0 ,0
Exp/Cntr=0.3,0.1

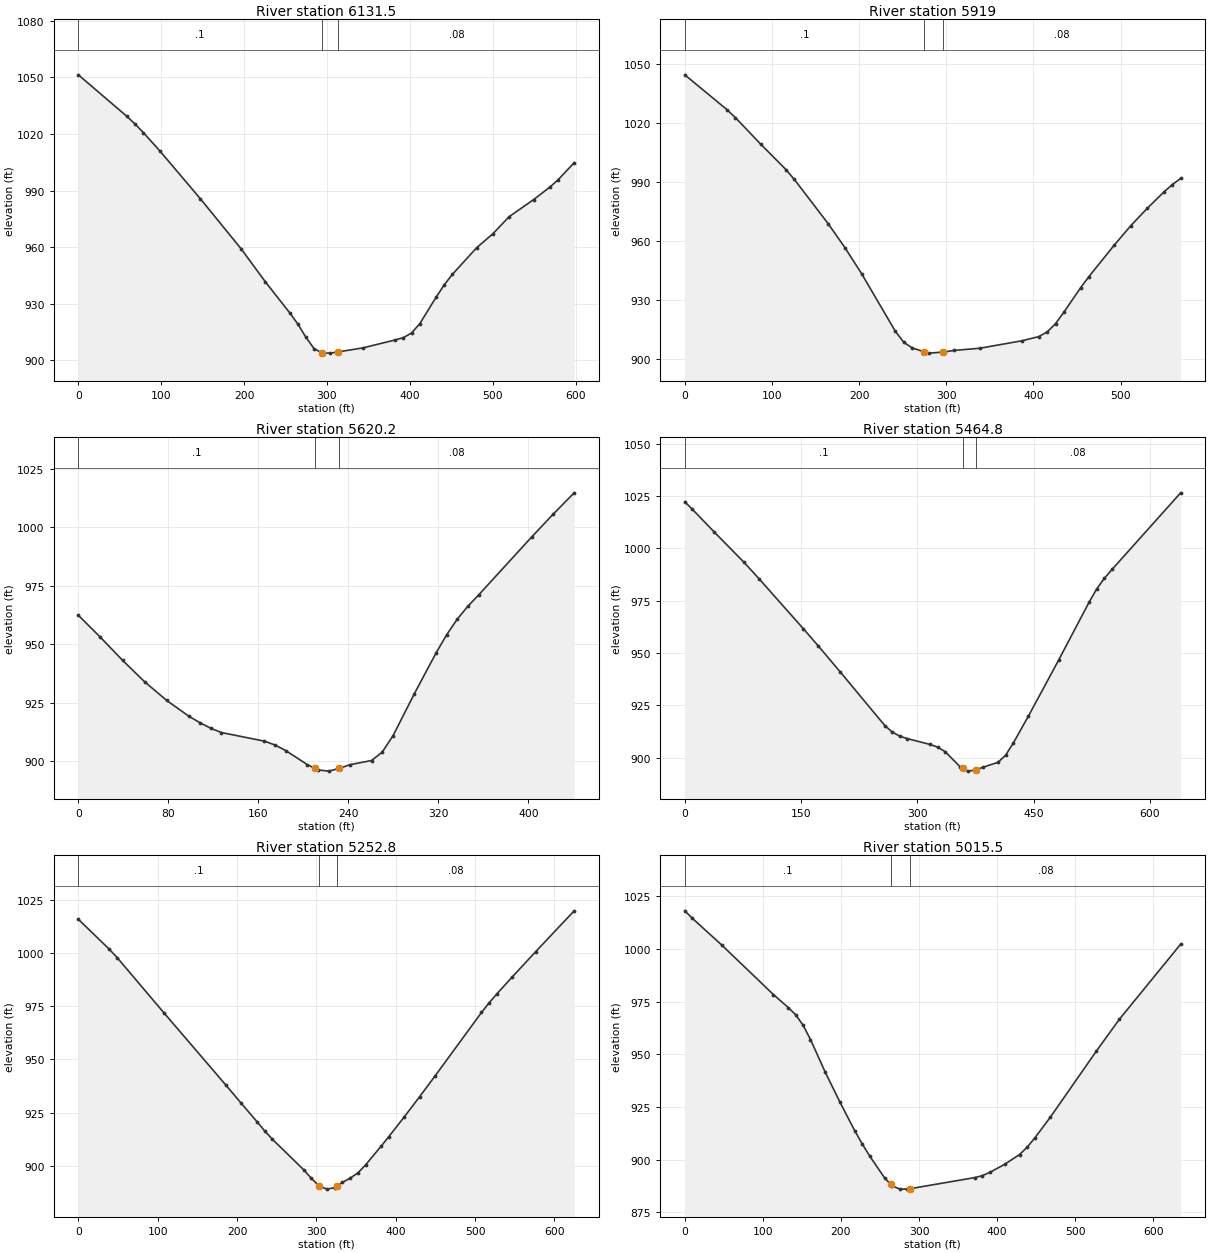
Type RM Length L Ch R = 1 ,6131.5  ,204.6,212.5,220
XS GIS Cut Line= 2
     1681204.595      627057.171     1680606.501       627073.28
#Sta/Elev= 30
       0 1051.28    58.8 1029.21    68.7 1025.12    78.5 1020.66    98.1 1011.11
   147.1  985.72   196.2  959.25   225.6  941.67     255  925.27   264.8  919.31
   274.6   912.3   284.4  906.27   294.2  903.92   304.1  903.87   313.9  904.55
   343.3  906.64   382.5  910.87   392.3  912.11   402.1  914.51     412  919.48
   431.6  933.38   441.4  939.95   451.2  945.53   480.6  959.68   500.2  967.08
   519.8  976.14   549.3  985.16   568.9  991.78   578.7  995.58   598.3 1004.72
#Mann= 3 , 0 , 0
       0      .1       0   294.2    .045       0   313.9     .08       0
Bank Sta=294.2,313.9
XS Rating Curve= 0 ,0
Exp/Cntr=0.3,0.1

Type RM Length L Ch R = 1 ,5919    ,303.4,298.8,293.3
XS GIS Cut Line= 3
     1681186.811       626943.61     1680781.441      626814.468
     1680646.667      626765.232
#Sta/Elev= 30
       0 1044.72    48.4 1026.96      58 1022.93      87 1009.42     116  996.45
   125.7  991.38   164.4  968.89   183.7  956.64     203  943.24   241.7  913.89
   251.4  908.29   261.1  905.46   274.5903.5469   280.3  902.84   296.6903.3816
   309.4  904.23   338.4  905.32   386.8  909.14   406.1  911.26   415.8  913.64
   425.4   917.9     435  923.74   454.1  936.15   463.7  941.89   492.4  957.71
   511.5  967.71   530.7   976.7   549.8  985.02   559.4  988.76   568.9   991.9
#Mann= 3 , 0 , 0
       0      .1       0   274.5    .045       0   296.6     .08       0
Bank Sta=274.5,296.6
XS Rating Curve= 0 ,0
Exp/Cntr=0.3,0.1

Type RM Length L Ch R = 1 ,5620.2  ,148.1,155.4,162.7
XS GIS Cut Line= 4
     1681110.675      626626.095      1681015.44      626574.843
     1680796.949      626556.188     1680692.706      626511.512
#Sta/Elev= 30
       0  962.34    19.7   952.9    39.3  943.08      59  933.86    78.6  925.89
    98.3  919.15   108.2  916.35   117.7  914.01   127.2  912.18   165.4   908.5
   174.9  906.83   184.4  904.46   203.5  898.48     210896.9063     213  896.18
   222.6  895.67   232.1  896.87   241.6  898.44   260.7  900.21   270.2  903.82
   279.8  910.85   298.8  928.85   317.9   946.1   327.4  953.96   336.9   960.7
   346.3   966.2   355.8  970.98     403  995.81     422  1005.5   440.8 1014.71
#Mann= 3 , 0 , 0
       0      .1       0     210    .045       0   232.1     .08       0
Bank Sta=210,232.1
XS Rating Curve= 0 ,0
Exp/Cntr=0.3,0.1

Type RM Length L Ch R = 1 ,5464.8  ,221,212.1,202.5
XS GIS Cut Line= 4
     1681314.315      626481.071      1681047.43      626460.529
     1680868.548      626383.133     1680691.501      626386.001
#Sta/Elev= 30
       0 1022.22     9.6 1018.72    38.2 1007.71    76.5  993.28    95.6  985.52
     153  961.55   172.1  953.39   200.8   940.8   258.1  915.26   267.7  912.18
   277.4   910.2   287.2  909.06   316.4  906.25   326.2     905   335.9  902.81
   355.4  895.48   358.6894.8339   365.1  893.52   375.6  894.09   384.6  895.37
   404.1  897.73   413.9  901.16   423.6  906.84   443.1  919.71   482.3  946.62
   521.6   974.3   531.4  980.62   541.3   985.7   551.1  989.89   639.6 1026.52
#Mann= 3 , 0 , 0
       0      .1       0   358.6    .045       0   375.6     .08       0
Bank Sta=358.6,375.6
XS Rating Curve= 0 ,0
Exp/Cntr=0.3,0.1

Type RM Length L Ch R = 1 ,5252.8  ,238.4,237.2,236.1
XS GIS Cut Line= 3
     1681303.034      626214.077     1680921.351      626214.291
     1680683.062       626262.83
#Sta/Elev= 30
       0 1015.88    39.2 1001.72    48.9  997.86   107.6  972.01     186  937.89
   205.5  929.27   225.1  920.73   234.9  916.34   244.7  912.37   283.8  898.18
   293.6   894.1   303.4   890.5   313.2  888.98     323  889.67   326.6  890.57
   332.8  892.12   342.5  894.14   352.3  896.58   362.1   900.4   381.7   909.2
   391.4  913.72   410.9  922.99   430.3  932.53   449.8   942.3   508.1  972.04
   517.9  976.66   527.6  980.85     547  988.81   576.2 1000.57   624.9 1019.85
#Mann= 3 , 0 , 0
       0      .1       0   303.4    .045       0   326.6     .08       0
Bank Sta=303.4,326.6
XS Rating Curve= 0 ,0
Exp/Cntr=0.3,0.1

Type RM Length L Ch R = 1 ,5015.5  ,270.7,267.7,262.8
XS GIS Cut Line= 4
     1681291.746      625901.123     1681069.272      625982.086
     1680877.482      625991.469     1680680.852      626054.118
#Sta/Elev= 30
       0 1018.13     9.5 1014.64    47.4 1001.86   113.6  978.33   132.6  972.17
     142  968.78   151.5   963.8     161     957   179.9  941.48   198.9  927.13
   217.8   913.6   227.3  907.38   236.8  901.68     256  891.23   263.8888.2156
   265.6  887.52   275.2     886   284.8  885.94   288.8886.1567   371.2  891.41
   380.8  892.29   390.4  893.84   409.6   897.7   428.8  902.37   438.6  905.88
   448.4   910.3   468.1  920.05     527   951.4   556.5  966.56   635.1 1002.28
#Mann= 3 , 0 , 0
       0      .1       0   263.8    .045       0   288.8     .08       0
Bank Sta=263.8,288.8
XS Rating Curve= 0 ,0
Exp/Cntr=0.3,0.1

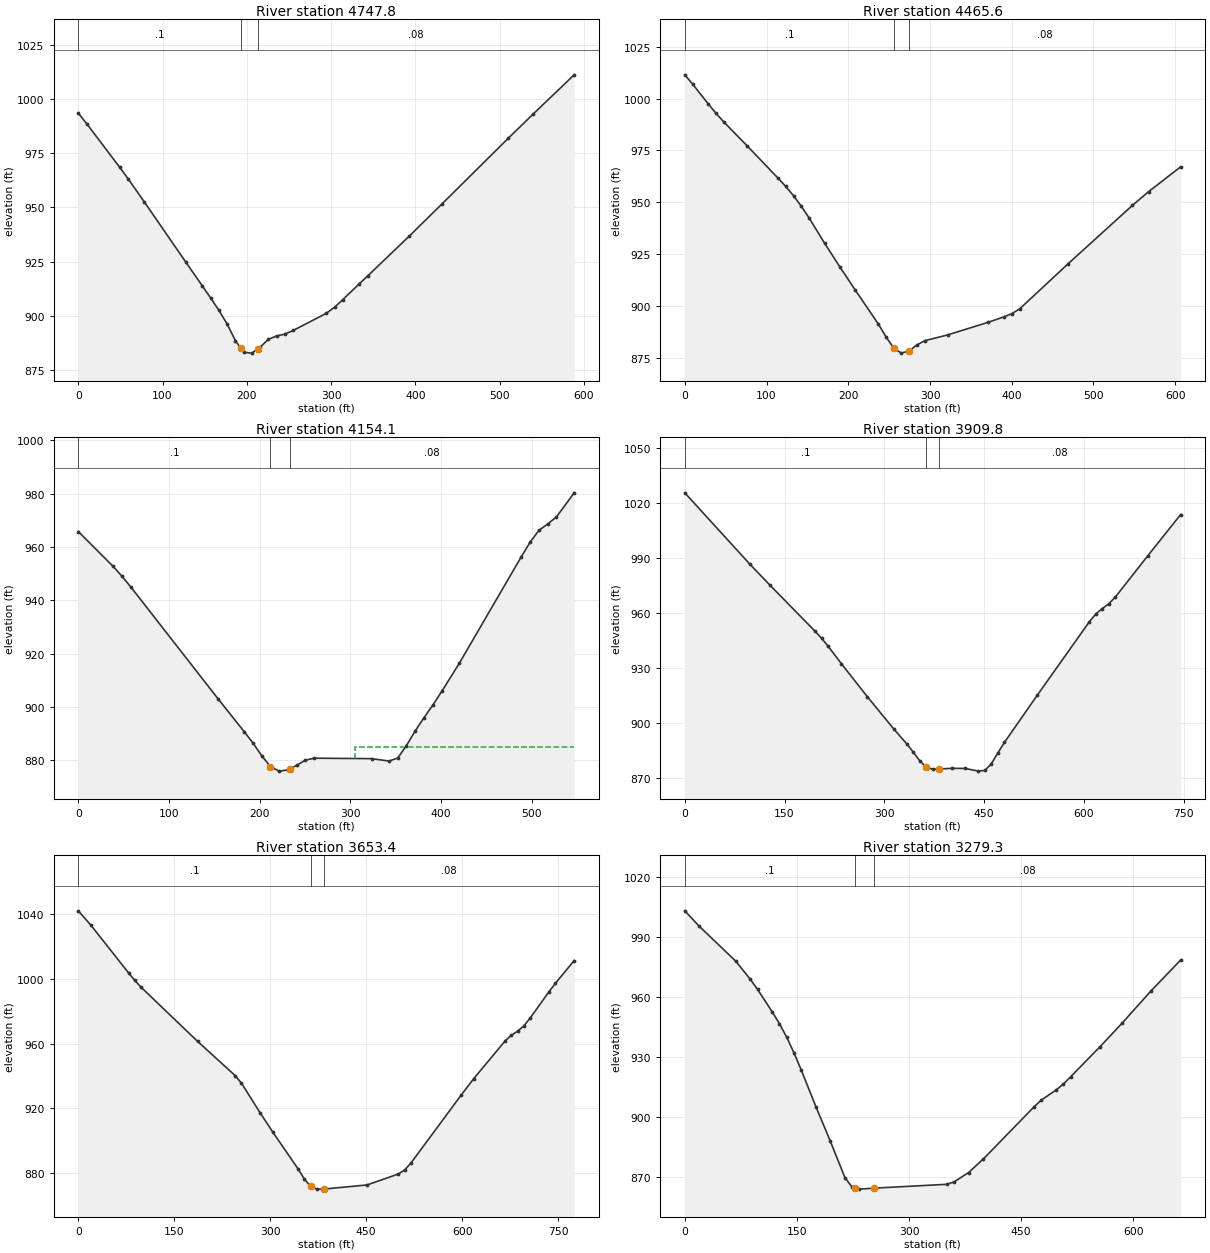
Type RM Length L Ch R = 1 ,4747.8  ,280.9,282.2,282.9
XS GIS Cut Line= 2
     1681129.869      625692.849     1680555.742      625822.598
#Sta/Elev= 30
       0  993.52     9.8  988.71      49  968.58    58.9  963.34    78.5  952.44
   127.5  924.79   147.2  913.75     157  908.21   166.8  902.55   176.6  896.18
   186.4  888.52   192.7  885.05   196.2  883.12     206  882.72   212.7884.6074
   215.8  885.48   225.6  889.07   235.4  890.67   245.2   891.5   255.1   893.2
   294.3  901.08   304.1  903.88   313.9   907.4   333.5  914.72   343.4  918.32
   392.4  936.58   431.6  951.56   510.1  981.82   539.6  992.97   588.6 1011.21
#Mann= 3 , 0 , 0
       0      .1       0   192.7    .045       0   212.7     .08       0
Bank Sta=192.7,212.7
XS Rating Curve= 0 ,0
Exp/Cntr=0.3,0.1

Type RM Length L Ch R = 1 ,4465.6  ,299.2,311.5,323.6
XS GIS Cut Line= 4
     1681127.206      625525.429     1680964.475      625447.467
     1680825.577      625472.375     1680575.991      625610.064
#Sta/Elev= 30
       0 1011.44     9.5 1007.01    28.5  997.52      38  992.98    47.5  988.82
      76  977.33     114  961.68   123.5  957.66     133  953.18   142.4  948.18
     152  942.53     171  930.31   189.8  918.83   208.7  907.64   236.9  891.28
   246.3   885.1   255.7  879.68   265.1  877.33   274.5  878.42   283.9  881.24
   293.3   883.3   321.6  886.11   370.7  892.13   390.4  894.79   400.2  896.37
     410  898.78     469  920.41   547.6  948.52   567.3   955.1   606.6   967.1
#Mann= 3 , 0 , 0
       0      .1       0   255.7    .045       0   274.5     .08       0
Bank Sta=255.7,274.5
XS Rating Curve= 0 ,0
Exp/Cntr=0.3,0.1

Type RM Length L Ch R = 1 ,4154.1  ,247.4,244.3,241
XS GIS Cut Line= 5
     1681152.549      625242.624     1680909.471      625150.464
     1680856.085      625144.681      1680798.27      625144.354
     1680634.427      625082.181
#Sta/Elev= 30
       0  965.81    38.5  952.72    48.1  949.05    57.8  945.06     154  903.12
   182.9  890.76   192.6  886.48   202.2  881.75   211.8  877.66   221.4  875.97
   231.1  876.42     233  876.76   240.7  878.14   250.3  880.07     260  880.82
   323.3  880.65   342.6  879.75   352.2  880.89   361.8  885.57   371.5  891.08
   381.2  896.05     391  900.79   400.7  905.86   420.2   916.5   488.3   956.3
     498  961.77   507.8  966.24   517.5  968.65   527.2   971.3   546.7  980.34
#Mann= 3 , 0 , 0
       0      .1       0   211.8    .045       0     233     .08       0
#XS Ineff= 2 , 0
       0                     305       0     885
Permanent Ineff=
       F       F
Bank Sta=211.8,233
XS Rating Curve= 0 ,0
Exp/Cntr=0.3,0.1

Type RM Length L Ch R = 1 ,3909.8  ,258,256.4,253.7
XS GIS Cut Line= 2
     1681378.251      625014.833     1680650.643      624852.071
#Sta/Elev= 30
       0 1025.57    98.1   986.5   127.5  975.35   196.2  949.86     206  946.02
   215.8  941.68   235.4  932.28   274.7  914.13   313.9  896.76   333.6  888.53
   343.4  884.05   353.2  879.28     363  875.81   372.8  874.62   382.6  874.74
   402.2  875.12   421.8  875.03   441.5  873.58   451.3  873.99   461.1  877.65
   470.9  883.61   480.7   889.3   529.8  914.91   608.2  955.08   618.1  959.43
   627.9  962.36   637.7     965   647.5  968.69   696.5  991.32   745.6 1013.72
#Mann= 3 , 0 , 0
       0      .1       0     363    .045       0   382.6     .08       0
Bank Sta=363,382.6
XS Rating Curve= 0 ,0
Exp/Cntr=0.3,0.1

Type RM Length L Ch R = 1 ,3653.4  ,373.1,374.1,369.2
XS GIS Cut Line= 2
     1681458.073      624739.168     1680688.877      624642.493
#Sta/Elev= 30
       0  1042.1    19.6 1033.25    78.5 1003.79    88.3  999.08    98.1   994.9
   186.4  961.49   245.3  940.28   255.1  935.64   284.6  917.11   304.2  905.35
   343.5  882.73   353.3  876.48   363.1  871.83   372.9  870.21   381.9  870.19
     384870.2444   451.4  872.77   500.5  879.55   510.3  882.07   520.1  886.36
   598.6   928.3   618.2  938.45   667.3  961.75   677.1  965.29   686.9  967.75
   696.7  971.11   706.6  975.95     736  992.22   745.8  997.28   775.2 1011.36
#Mann= 3 , 0 , 0
       0      .1       0   363.1    .045       0     384     .08       0
Bank Sta=363.1,384
XS Rating Curve= 0 ,0
Exp/Cntr=0.3,0.1

Type RM Length L Ch R = 1 ,3279.3  ,135.3,134.6,135.2
XS GIS Cut Line= 3
     1681349.158      624334.672     1680872.094      624339.413
     1680695.599      624398.853
#Sta/Elev= 30
       0 1003.24    19.5  995.44    68.2     978    87.6  968.95    97.4  963.82
   116.8  952.71   126.6  946.67   136.3  939.94     146  932.11   155.8  923.47
   175.3  905.16   194.7  887.78   214.2  869.55   223.9  864.72   227.3  864.39
   233.7  863.77   253.3864.2623   350.5  866.19   360.2  867.39   379.7   872.1
   399.2   878.8   467.4  905.09   477.1  908.44   496.7  913.45   506.5  916.47
   516.3  920.12   555.5  935.16   584.9  946.89   624.1  963.28   663.3  978.57
#Mann= 3 , 0 , 0
       0      .1       0   227.3    .045       0   253.3     .08       0
Bank Sta=227.3,253.3
XS Rating Curve= 0 ,0
Exp/Cntr=0.3,0.1

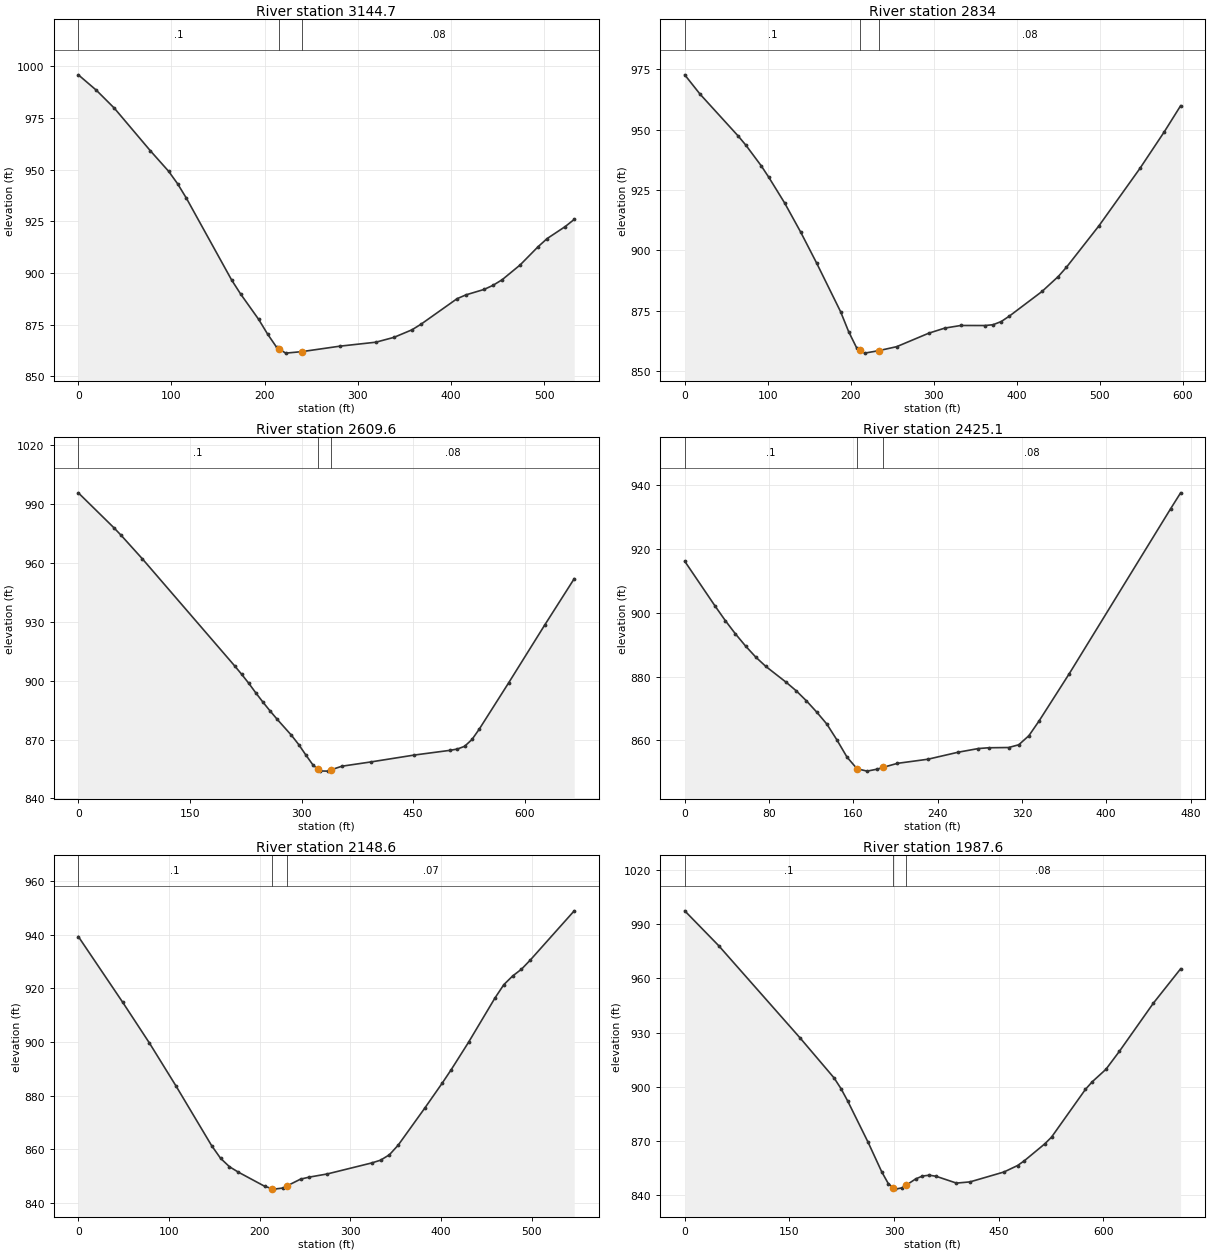
Type RM Length L Ch R = 1 ,3144.7  ,305.7,310.7,314.3
XS GIS Cut Line= 2
     1681310.636      624215.638     1680778.568      624199.019
#Sta/Elev= 30
       0  995.76    19.4  988.29    38.7  979.62    77.4  959.02    96.8  949.22
   106.5  943.17   116.1  936.07   164.5  896.67   174.2  889.86   193.6  877.58
   203.2  870.46   212.9  864.09   215.9  863.22   222.6  861.29   239.9862.0076
   280.7  864.65   319.4  866.57   338.8  868.91   358.1  872.55   367.8  875.25
   406.5  887.58   416.2  889.46   435.5  892.06   445.2  894.07   454.9  896.74
   474.3  903.92   493.6  912.75   503.3  916.66   522.6  922.43   532.3   925.9
#Mann= 3 , 0 , 0
       0      .1       0   215.9    .045       0   239.9     .08       0
Bank Sta=215.9,239.9
XS Rating Curve= 0 ,0
Exp/Cntr=0.3,0.1

Type RM Length L Ch R = 1 ,2834    ,224.7,224.3,221.2
XS GIS Cut Line= 4
     1681290.887      623978.631     1681191.926       623929.16
     1680947.309       623872.42     1680714.064      623908.318
#Sta/Elev= 30
       0  972.69    18.4  964.71    64.5   947.3    73.8  943.48    92.2  934.98
   101.4  930.18   120.3  919.64   139.6   907.6   158.9  894.72   187.9  874.48
   197.6  866.21   207.2  859.53   211.6  858.54   216.9  857.34     234858.3706
   255.5  860.02   294.1   865.6   313.5  867.72   332.8   868.8   361.8  868.78
   371.6  869.11   381.4  870.42   391.2  872.67   430.6  882.89   450.2  889.09
   460.1  892.94   499.4  910.18   548.6  933.88   578.1  949.12   597.7  959.88
#Mann= 3 , 0 , 0
       0      .1       0   211.6    .045       0     234     .08       0
Bank Sta=211.6,234
XS Rating Curve= 0 ,0
Exp/Cntr=0.3,0.1

Type RM Length L Ch R = 1 ,2609.6  ,178.5,184.5,190.5
XS GIS Cut Line= 4
     1681407.197      623888.247     1681190.813      623700.476
     1680970.669      623665.342     1680842.207      623574.952
#Sta/Elev= 30
       0  995.71    47.8  977.92    57.3  974.16      86  962.11   210.1  907.55
   219.6  903.22   229.2  898.61   238.8  893.66   248.3  888.99   257.8  884.55
   267.4  880.27   286.5  872.16   296.2  867.46   305.9  862.09   315.6  856.93
     322855.0062   325.3  854.01     335  853.92     340854.6284   354.3  856.43
   393.1   858.6   451.3   862.1   499.7  864.52   509.4  865.17   519.2  866.57
   529.1  870.05   538.9  875.34   578.2   898.8   627.2  928.57   666.5  951.96
#Mann= 3 , 0 , 0
       0      .1       0     322    .045       0     340     .08       0
Bank Sta=322,340
XS Rating Curve= 0 ,0
Exp/Cntr=0.3,0.1

Type RM Length L Ch R = 1 ,2425.1  ,282.2,276.5,270.6
XS GIS Cut Line= 3
     1681393.436      623555.316     1681268.536      623547.129
     1680953.741      623405.029
#Sta/Elev= 30
       0  916.08    28.9  902.01    38.5  897.51    48.1  893.35    57.8  889.52
    67.4  886.08      77  883.15    96.3  878.19   105.9   875.5   115.5  872.38
   125.2  868.89   134.8  865.14   144.4  860.17     154  854.78   163.5  851.13
   173.1  850.39   182.7  851.01   188.1851.5556   201.9  852.83   230.7  854.11
   259.5  856.31   278.7  857.46   288.3   857.7   307.4  857.78     317  858.64
   326.6  861.48   336.2  866.06     365  880.93     461  932.45   470.6  937.49
#Mann= 3 , 0 , 0
       0      .1       0   163.5    .045       0   188.1     .08       0
Bank Sta=163.5,188.1
XS Rating Curve= 0 ,0
Exp/Cntr=0.3,0.1

Type RM Length L Ch R = 1 ,2148.6  ,164.6,161.1,156.7
XS GIS Cut Line= 3
     1681471.191      623295.477      1681133.14      623237.722
     1680931.348       623266.91
#Sta/Elev= 30
       0  939.37      49  914.82    78.4  899.67   107.8  883.61     147  861.42
   156.8  856.73   166.6  853.58   176.4  851.56   205.8  846.22   213.6845.4266
   215.6  845.22   225.4  845.62   229.6846.3421     245  848.94   254.8  849.71
   274.4  850.87   323.4  854.97   333.2     856     343  858.02   352.7  861.62
   381.8  875.32   401.2  884.71   410.9  889.61   430.3  899.97   459.5  916.51
   469.2  921.44   478.9  924.66   488.6  927.18   498.3  930.58   546.8  948.95
#Mann= 3 , 0 , 0
       0      .1       0   213.6    .045       0   229.6     .07       0
Bank Sta=213.6,229.6
XS Rating Curve= 0 ,0
Exp/Cntr=0.3,0.1

Type RM Length L Ch R = 1 ,1987.6  ,152.1,151.3,150.2
XS GIS Cut Line= 2
     1681619.067      623110.484     1680908.192      623110.602
#Sta/Elev= 30
       0  997.38    48.7  978.09   165.6  926.93   214.2  904.86     224     899
   233.7  892.07   262.9  869.27   282.4  852.95   292.1  846.23   299.1  844.19
   301.9  843.37   311.6  844.08   317.1845.4521   331.1  849.03   340.8  850.61
   350.6  851.07   360.3  850.49   389.5  846.71     409  847.38   457.7  852.86
   477.2  856.44   486.9  859.08   516.1  868.41   525.8  872.13   574.5  898.61
   584.3  902.82   603.8  909.67   623.2  919.68   671.9  946.32   710.9   965.3
#Mann= 3 , 0 , 0
       0      .1       0   299.1    .045       0   317.1     .08       0
Bank Sta=299.1,317.1
XS Rating Curve= 0 ,0
Exp/Cntr=0.3,0.1

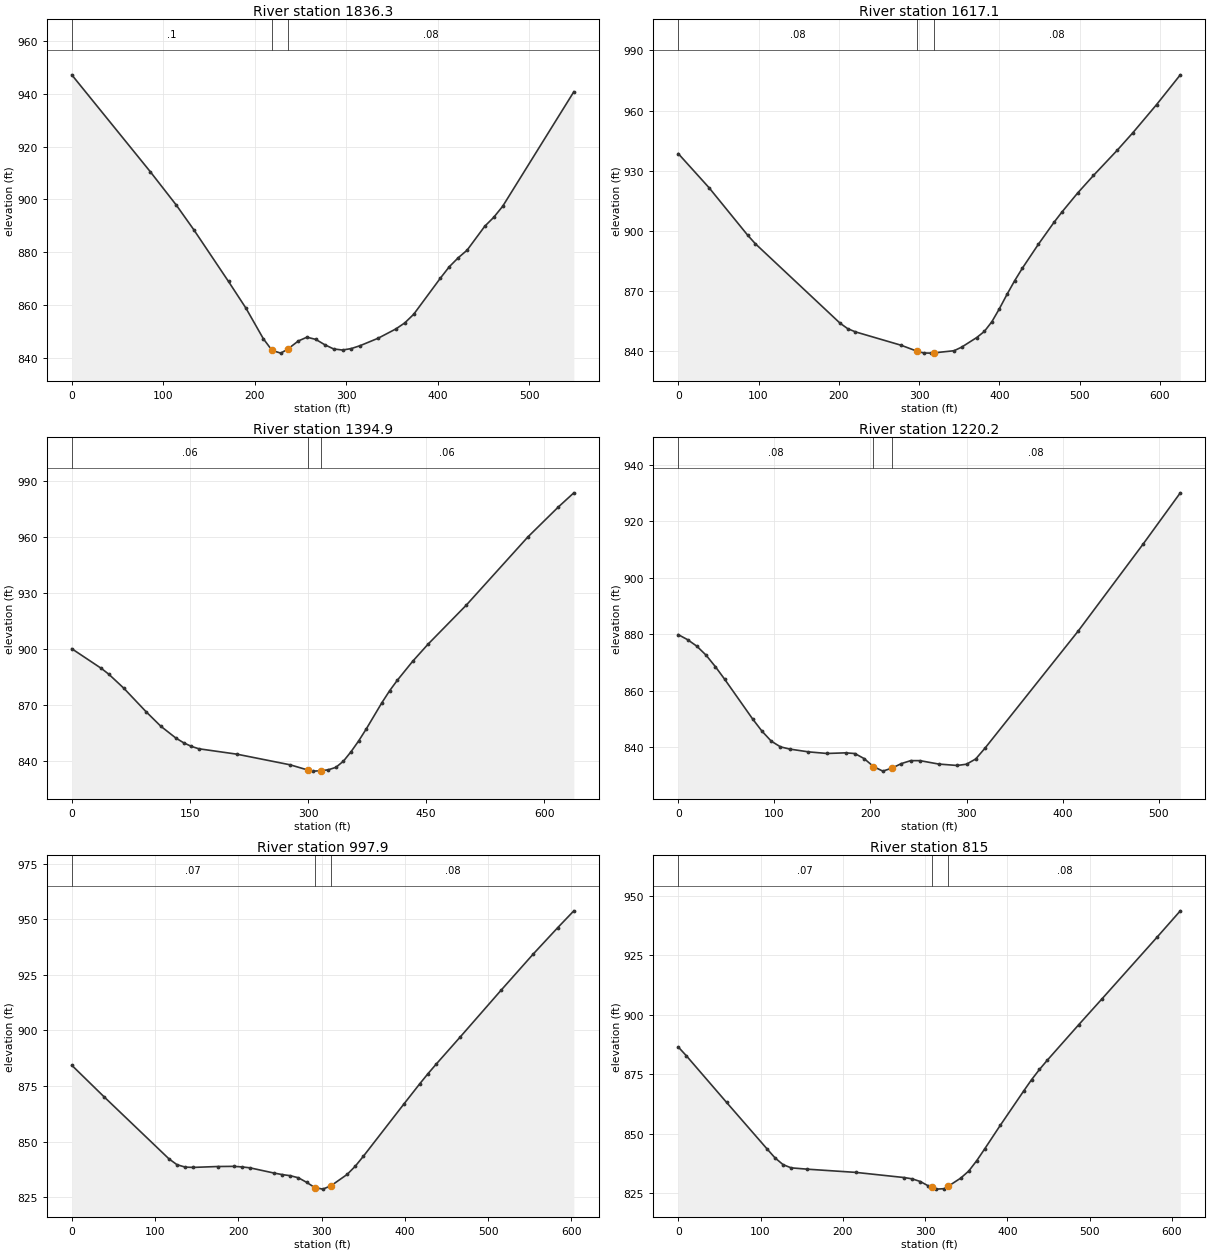
Type RM Length L Ch R = 1 ,1836.3  ,222.7,219.1,215.3
XS GIS Cut Line= 3
     1681518.281      622952.928     1681261.514      622963.884
      1680969.88      622967.433
#Sta/Elev= 30
       0  947.21    85.7  910.57   114.2   897.9   133.3  888.58   171.3  868.95
   190.4  858.82   209.4  847.25   218.9  842.85   228.4  841.82   235.9   843.3
   247.5   846.4     257  847.86   266.7  847.01   276.4  845.02   286.2   843.4
   295.9  842.99   305.6  843.56   315.3  844.67   334.8  847.46   354.2  850.98
   363.9  853.26   373.7  856.54   402.8  870.19   412.6  874.54   422.3  877.92
     432  880.79   451.4  889.89   461.2  893.27   470.9  897.42   548.7   940.8
#Mann= 3 , 0 , 0
       0      .1       0   218.9    .045       0   235.9     .08       0
Bank Sta=218.9,235.9
XS Rating Curve= 0 ,0
Exp/Cntr=0.3,0.1

Type RM Length L Ch R = 1 ,1617.1  ,219.7,222.2,224.4
XS GIS Cut Line= 4
     1681533.361      622772.123     1681295.346      622740.929
     1681120.124      622777.124     1680914.438       622795.56
#Sta/Elev= 30
       0  938.53    38.4  921.49    86.4  897.84      96  893.55   201.6  853.86
   211.2   851.1   220.8  849.52   277.7  842.84   297.8839.8262     306  838.98
   314.8  838.91   318.8839.0438   343.6  840.11     353  841.88   371.9   846.7
   381.3  849.72   390.7  854.57   400.1  861.08   409.6  868.25     419  874.97
   428.8  881.36   448.5  893.16   468.1  904.19     478  909.34   497.6  918.85
   517.3   927.6   546.8  940.15   566.5  948.99     596  963.02   625.5  977.85
#Mann= 3 , 0 , 0
       0     .08       0   297.8    .045       0   318.8     .08       0
Bank Sta=297.8,318.8
XS Rating Curve= 0 ,0
Exp/Cntr=0.3,0.1

Type RM Length L Ch R = 1 ,1394.9  ,185.7,174.8,162.7
XS GIS Cut Line= 4
     1681474.618        622581.4     1681369.143       622518.96
     1681138.147        622541.9     1680896.523      622688.781
#Sta/Elev= 30
       0  900.02    37.7  889.44    47.1  886.35      66  878.91    94.3  866.32
   113.1  858.52   132.2   852.2   141.9  849.71   151.6  847.79   161.3  846.47
   209.6  843.58   277.3  837.88   299.6  835.11   306.3   834.5     316   834.7
   325.7  835.21   335.4  836.54     345  839.86   354.7  844.95   364.4  850.75
   374.2  857.27   393.7  871.08   403.5  877.47   413.2  883.05   432.7  893.21
   452.2  902.37     501  923.37     579  959.79     618  975.96   637.5  983.46
#Mann= 3 , 0 , 0
       0     .06       0   299.6    .045       0     316     .06       0
Bank Sta=299.6,316
XS Rating Curve= 0 ,0
Exp/Cntr=0.3,0.1

Type RM Length L Ch R = 1 ,1220.2  ,226.7,222.2,216.5
XS GIS Cut Line= 2
     1681361.032      622247.713      1680927.82      622539.842
#Sta/Elev= 30
       0  879.92     9.7  878.14    19.4  875.82      29  872.64    38.7  868.56
    48.4  864.09    77.4  850.08    87.1  845.78    96.8  842.22   106.4   840.2
   116.1  839.41   135.5  838.43   154.8  837.86   174.2  838.08   183.8  837.84
   193.5  836.04   203.2  833.23   212.9  831.61   222.6   832.7   232.2  834.28
   241.9  835.32   251.6  835.32   270.9  834.12   290.3  833.61     300  834.06
   309.6  835.92   319.3  839.76   416.1  881.13   483.8  911.97   522.5   930.1
#Mann= 3 , 0 , 0
       0     .08       0   203.2    .045       0   222.6     .08       0
Bank Sta=203.2,222.6
XS Rating Curve= 0 ,0
Exp/Cntr=0.3,0.1

Type RM Length L Ch R = 1 ,997.9   ,186.9,183,178.4
XS GIS Cut Line= 2
     1681197.074      622060.982     1680787.844      622503.818
#Sta/Elev= 30
       0  884.33    38.9  870.09   116.7   842.2   126.4  839.55   136.2  838.48
   145.9  838.34   175.1  838.74   194.5  838.81   204.2  838.57     214  838.15
   243.1  835.78   252.9   835.1   262.6   834.6   272.3  833.65     282  831.63
   291.8  829.29   301.5  828.56   311.2  830.04   330.7  835.17   340.4  838.84
   350.1   843.3   398.7  866.79   418.2  876.11   427.9  880.57   437.6   884.8
   466.8  897.17   515.4  918.02   554.3  934.43   583.5  946.22     603  953.85
#Mann= 3 , 0 , 0
       0     .07       0   291.8    .045       0   311.2     .08       0
Bank Sta=291.8,311.2
XS Rating Curve= 0 ,0
Exp/Cntr=0.3,0.1

Type RM Length L Ch R = 1 ,815     ,148.8,148.3,147
XS GIS Cut Line= 3
     1681012.133       621912.96     1680819.223      622220.281
     1680719.098      622446.469
#Sta/Elev= 30
       0  886.48     9.8   882.8    58.8  863.14   107.9  843.61   117.7   839.8
   127.5  836.96   137.3  835.63   156.9  835.07   215.8  833.72   274.6  831.55
   284.4     831   294.2  829.88     304  828.03   308.4  827.42   313.8  826.68
   323.4  826.87   328.4  827.95   343.2  831.29     353  834.26   362.8  838.66
   372.4  843.58   391.4  853.52   419.9  867.98   429.4   872.7     439     877
   448.5  880.89   486.5  895.74   515.1  906.74   581.7  932.55   610.2  943.73
#Mann= 3 , 0 , 0
       0     .07       0   308.4    .045       0   328.4     .08       0
Bank Sta=308.4,328.4
XS Rating Curve= 0 ,0
Exp/Cntr=0.3,0.1