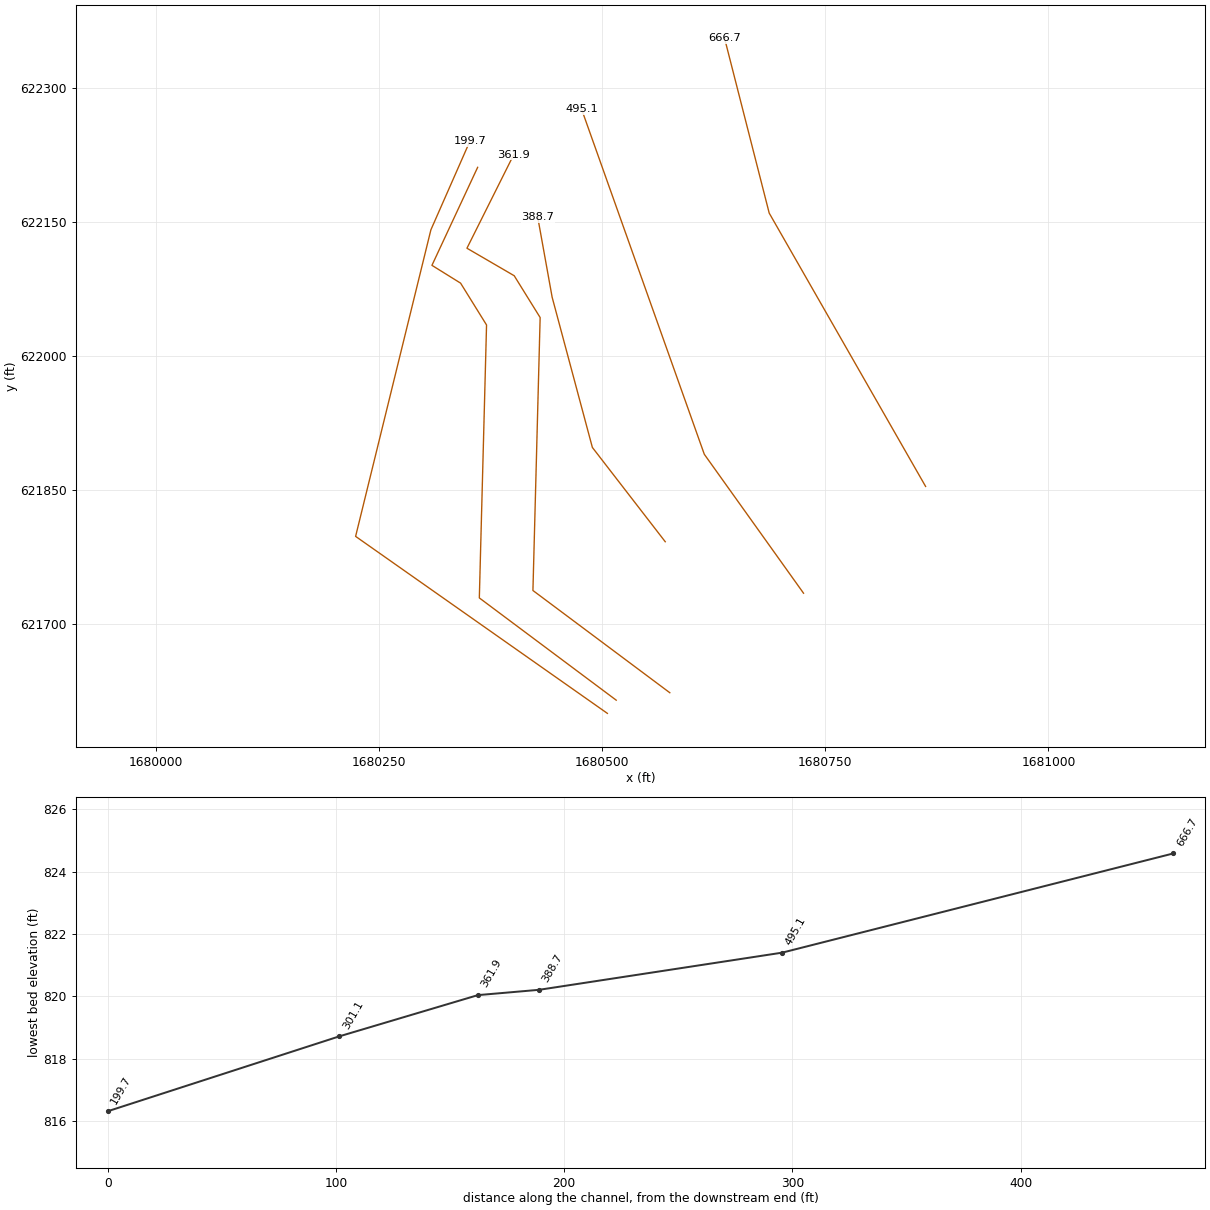
HEC-RAS study CMPRN.prj: CMPRN

--- CMPRN.g01 (geometry) --- (continued)

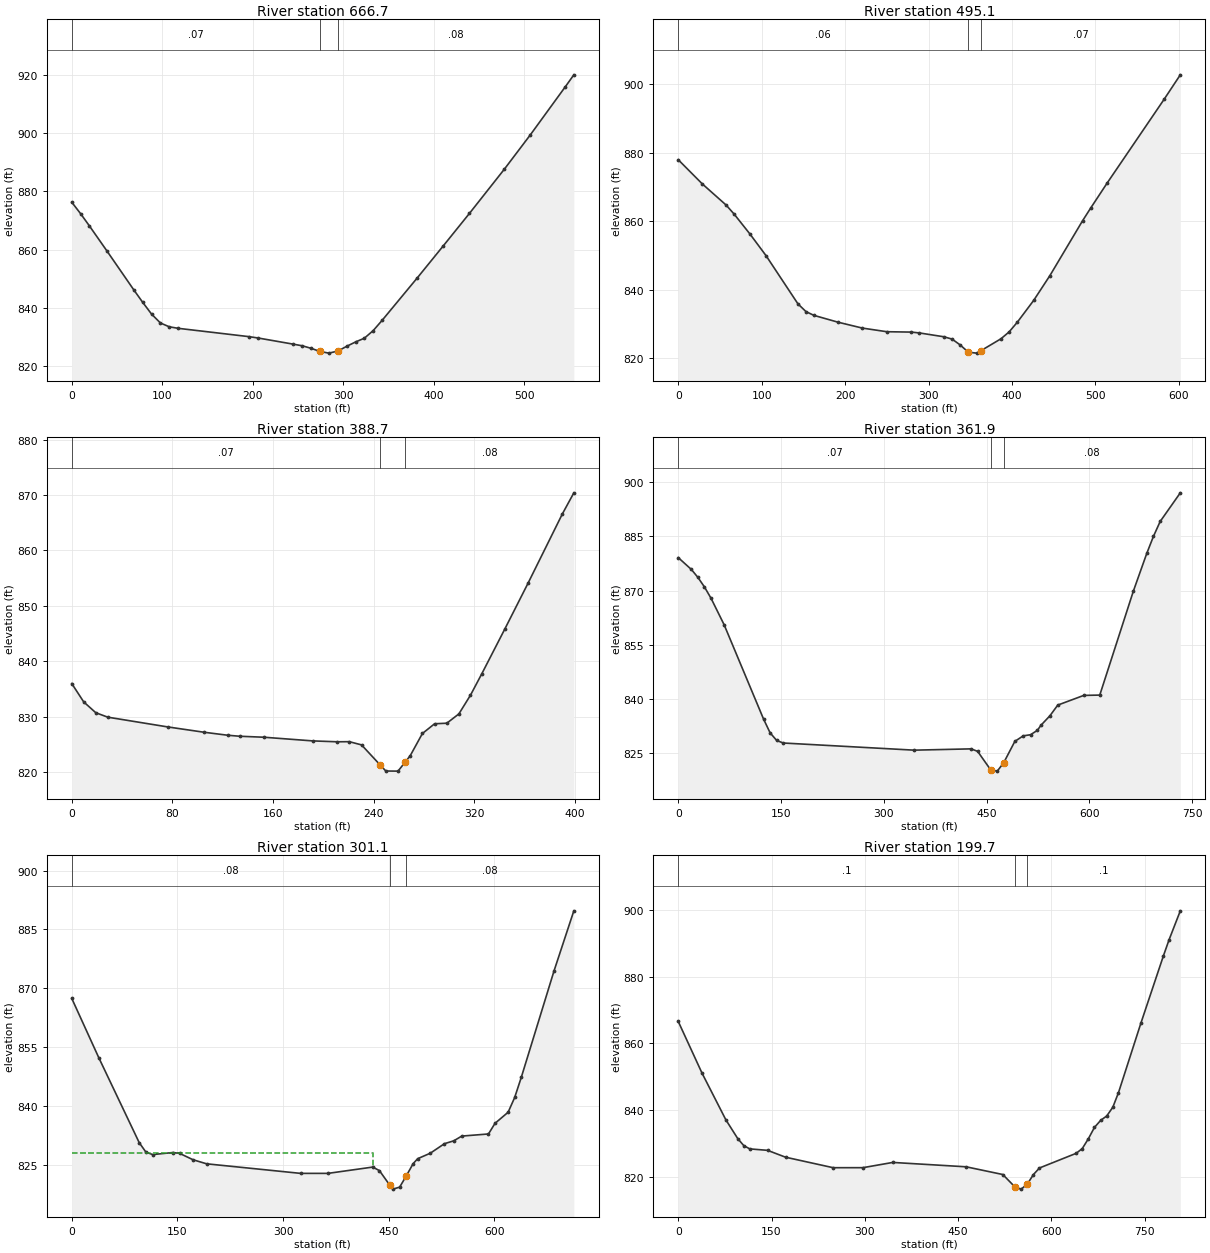
Type RM Length L Ch R = 1 ,666.7   ,175.4,171.5,167.3
XS GIS Cut Line= 3
     1680862.294      621853.764     1680687.029      622160.067
     1680636.995      622355.963
#Sta/Elev= 30
       0  876.28     9.8  872.34    19.6  868.12    39.2  859.44    68.6  846.24
    78.4  841.99    88.2  837.96      98  834.91   107.8   833.6   117.6  833.08
   196.1  830.22   205.9  829.77   245.1  827.64   254.9  827.09   264.7  826.22
   274.5  825.14   284.3  824.58   294.4  825.31   303.9  826.91   313.7   828.4
   323.5  829.69   333.3  832.31   343.1   835.8   381.8  850.28   410.7  861.31
   439.6  872.42   478.1  887.53     507  899.36   545.5  915.76   555.1  919.92
#Mann= 3 , 0 , 0
       0     .07       0   274.5    .045       0   294.4     .08       0
Bank Sta=274.5,294.4
XS Rating Curve= 0 ,0
Exp/Cntr=0.3,0.1

Type RM Length L Ch R = 1 ,495.1   ,108.2,106.5,104.5
XS GIS Cut Line= 3
       1680725.5      621734.081     1680614.278      621889.785
     1680476.781       622276.46
#Sta/Elev= 30
       0  877.95    28.7  870.91    57.4  864.69      67  862.05    86.1  856.18
   105.2  849.91   143.5  835.79   153.1  833.54   162.6  832.44   191.4  830.45
   220.7  828.72     250  827.66   279.3  827.55   289.1   827.3   318.4  826.18
   328.2   825.5   337.9  823.79   347.7  821.67   357.5   821.4   362.9822.1341
   386.8   825.6   396.6  827.62   406.3  830.42   425.9  836.79   445.4  844.06
   484.5  860.08   494.3  863.82   513.8  871.05   582.2  895.58   601.7  902.77
#Mann= 3 , 0 , 0
       0     .06       0   347.7    .045       0   362.9     .07       0
Bank Sta=347.7,362.9
XS Rating Curve= 0 ,0
Exp/Cntr=0.3,0.1

Type RM Length L Ch R = 1 ,388.7   ,33,26.8,20.8
XS GIS Cut Line= 4
     1680570.489      621791.795     1680488.823      621897.457
     1680443.746      622065.815     1680427.541      622155.767
#Sta/Elev= 28
       0     836     9.5  832.69    19.1  830.74    28.6  829.94    76.3  828.18
   104.9  827.23     124  826.68   133.5   826.5   152.9  826.32   191.6  825.66
     211   825.5   220.7  825.52   230.4  824.94   245.4821.2737   249.7  820.23
   259.4  820.21     265821.8151   269.1  822.99   278.8     827   288.5  828.75
   298.2  828.85   307.8  830.53     317   833.9   326.1   837.8   344.4  845.87
   362.7  854.06   390.1   866.6   399.2  870.39
#Mann= 3 , 0 , 0
       0     .07       0   245.4    .045       0     265     .08       0
Bank Sta=245.4,265
XS Rating Curve= 0 ,0
Exp/Cntr=0.3,0.1

Type RM Length L Ch R = 1 ,361.9   ,60.7,60.7,60.8
XS GIS Cut Line= 6
     1680575.609      621622.554     1680422.208      621737.133
     1680430.296      622043.041     1680401.216      622089.916
     1680348.265      622120.732     1680400.782      622225.766
#Sta/Elev= 30
       0  879.12    19.2  875.83    28.7  873.64    38.3  870.98    47.9  867.85
      67  860.52   124.4  834.48     134  830.65   143.6  828.53   153.2  827.82
   344.3  825.84   427.3   826.2   436.8  825.51   455.9  820.38   465.5  820.04
     475  822.42   491.1  828.27   503.3   829.8     514  830.11     524  831.33
   529.1  832.71   542.3  835.36   553.7  838.31   591.6  840.99     615  841.08
     664  869.84   683.6   880.3   693.3  884.99   703.1  889.11   732.5  897.04
#Mann= 3 , 0 , 0
       0     .07       0   455.9    .045       0     475     .08       0
Bank Sta=455.9,475
XS Rating Curve= 0 ,0
Exp/Cntr=0.3,0.1

Type RM Length L Ch R = 1 ,301.1   ,106.3,101.5,95.6
XS GIS Cut Line= 6
     1680515.539      621614.221     1680362.139        621728.8
     1680370.227      622034.707     1680341.147      622081.582
     1680309.029      622101.548     1680360.251      622211.391
#Sta/Elev= 30
       0   867.4    38.3  852.29    95.7   830.6   105.3  828.16   114.9  827.54
   143.6  828.06   153.2  827.84   172.3  826.21   191.5  825.18   324.9  822.74
   363.7  822.74   427.3  824.35   436.8  823.44   451.2819.8084   455.9  818.72
   465.5  819.23     475  822.13   484.6  825.21   491.1  826.49     509  827.89
   529.1  830.32   542.3  831.05   553.7  832.26   591.6   832.8   600.9  835.52
   619.5  838.35   628.8  842.11   638.2  847.26   684.8   874.5   712.8  889.76
#Mann= 3 , 0 , 0
       0     .08       0   451.2    .045       0     475     .08       0
#XS Ineff= 2 , 0
       0   427.3     828               0
Permanent Ineff=
       F       F
Bank Sta=451.2,475
XS Rating Curve= 0 ,0
Exp/Cntr=0.3,0.1

Type RM Length L Ch R = 1 ,199.7   ,214.8,199.7,183.6
XS GIS Cut Line= 4
     1680505.651      621599.412     1680223.478      621797.779
     1680307.859       622141.38     1680351.571      622240.688
#Sta/Elev= 30
       0  866.58    38.3  851.06    76.6  837.08    95.8  831.43   105.4  829.36
     115  828.38   143.7  827.94   172.5  825.89   249.1  822.74     297  822.75
   344.9  824.32   462.9  823.01   521.8   820.7   541.5  816.94   551.3  816.32
   561.1  817.78     571  820.68   580.8  822.66   639.8  827.05   649.6  828.48
   659.4  831.42   669.2  834.83   679.1  836.92   688.9  838.24   698.7  840.86
   707.8  845.23   743.9   866.1   780.1  886.26   789.2  891.09   807.2  899.72
#Mann= 3 , 0 , 0
       0      .1       0   541.5    .045       0   561.1      .1       0
Bank Sta=541.5,561.1
XS Rating Curve= 0 ,0
Exp/Cntr=0.3,0.1

Chan Stop Cuts=-1
Use User Specified Reach Order=0
Composite Channel Slope=5